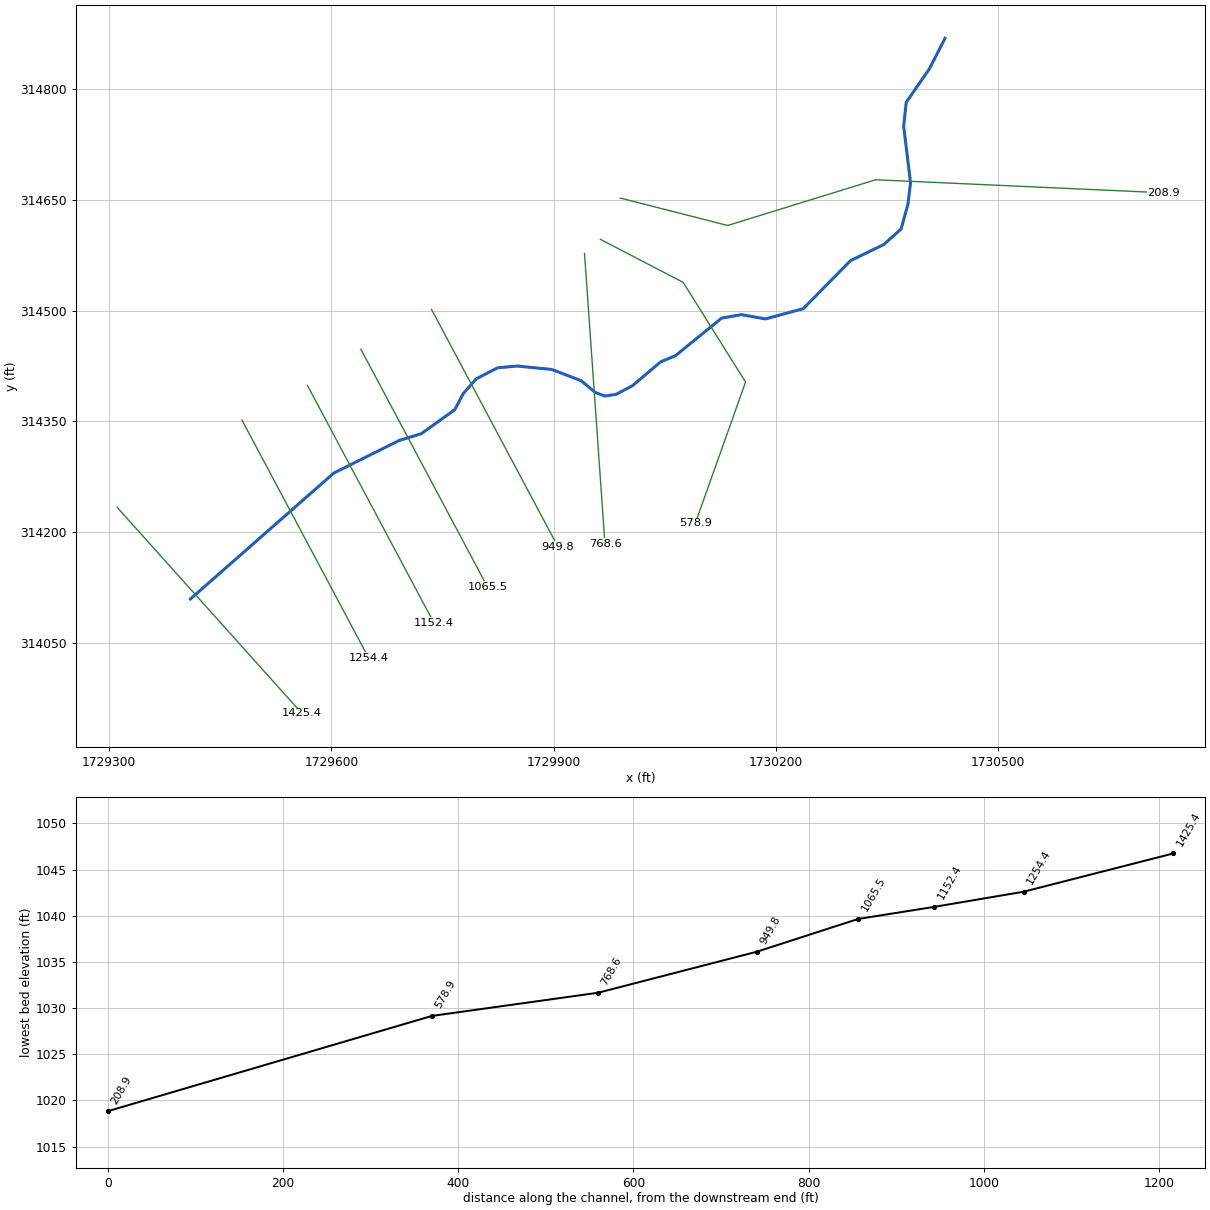
--- ADKINSFRK.prj (project) ---

Proj Title=ADKINSFRK
Current Plan=p01
Default Exp/Contr=0,0
English Units
Geom File=g01
Flow File=f01
Plan File=p01
BEGIN DESCRIPTION:
END DESCRIPTION:
DSS Export Rating Curves= 0
DSS Export Rating Curve Sorted= 0
DSS Export Volume Flow Curves= 0
DXF OffsetX= 0
DXF OffsetY= 0
DXF ScaleX= 0
DXF ScaleY= 0

--- ADKINSFRK.p01 (plan) ---

Plan Title=Floodplain
Program Version=4.00
Geom File=g01
Flow File=f01
K Sum by GR=0
Std Step Tol=0.01
Critical Tol=0.01
Num of Std Step Trials=20
Max Error Tol=0.3
Flow Tol Ratio=0.001
Split Flow NTrial=30
Split Flow Tol=0.02
Split Flow Ratio=0.02
Log Output Level=0
Friction Slope Method=1
Unsteady Friction Slope Method=2
Unsteady Bridges Friction Slope Method=1
Global Log Level=0
CheckData=False
Run HTab=0
Run UNet=0
Run PostProcess=0
UNET Theta=0
UNET Theta Warmup=0
UNET ZTol=0
UNET ZSATol=0
UNET MxIter=0
UNET MaxInSteps=0
UNET DtIC=0
UNET DtMin=0
UNET MaxCRTS=0
UNET WFStab=0
UNET SFStab=0
UNET WFX=0
UNET SFX=0
UNET DSS MLevel=0
UNET DZMax Abort=0
UNET Convert EG Bridges=0
UNET Use Existing IB Tables=0
UNET Froude Limit=0
UNET Froude Power=0
Write IC File=0
Echo Input=False
Echo Output=False
Write Detailed=0

--- ADKINSFRK.f01 (steady flow) ---

Flow Title=NFF Regression Equation
Program Version=4.00
Number of Profiles=1
Profile Names=P100yr
River Rch & RM=ADKINSFRK,Main      ,1425.4
888.6882
River Rch & RM=ADKINSFRK,Main      ,208.9
897.6510
Boundary for River Rch & Prof#=ADKINSFRK,Main      ,1
Up Type=0
Dn Type=3
Dn Slope=0.019353

--- ADKINSFRK.g01 (geometry) ---

Geom Title=USGS 10m DEM
Program Version=4.10

River Reach=ADKINSFRK       ,Main
Reach XY= 30
     1729409.795      314109.872     1729603.215      314280.128
     1729691.238       314324.14     1729721.351      314333.405
     1729766.522      314365.835     1729778.104      314387.841
     1729795.477       314407.53     1729824.432      314422.587
      1729851.07      314424.903     1729897.398      314420.271
     1729936.778      314405.214     1729956.467      314388.999
     1729969.207      314384.366     1729984.264      314386.683
      1730006.27      314398.265      1730044.49      314430.694
      1730064.18      314438.802     1730126.723      314489.763
     1730153.361      314494.396     1730185.791      314488.605
     1730236.752      314502.503     1730300.453      314567.362
     1730345.623      314589.368     1730368.787      314610.216
     1730378.053      314643.804     1730381.527      314672.759
     1730372.262        314749.2     1730375.736       314781.63
     1730407.008        314826.8     1730428.016      314868.031

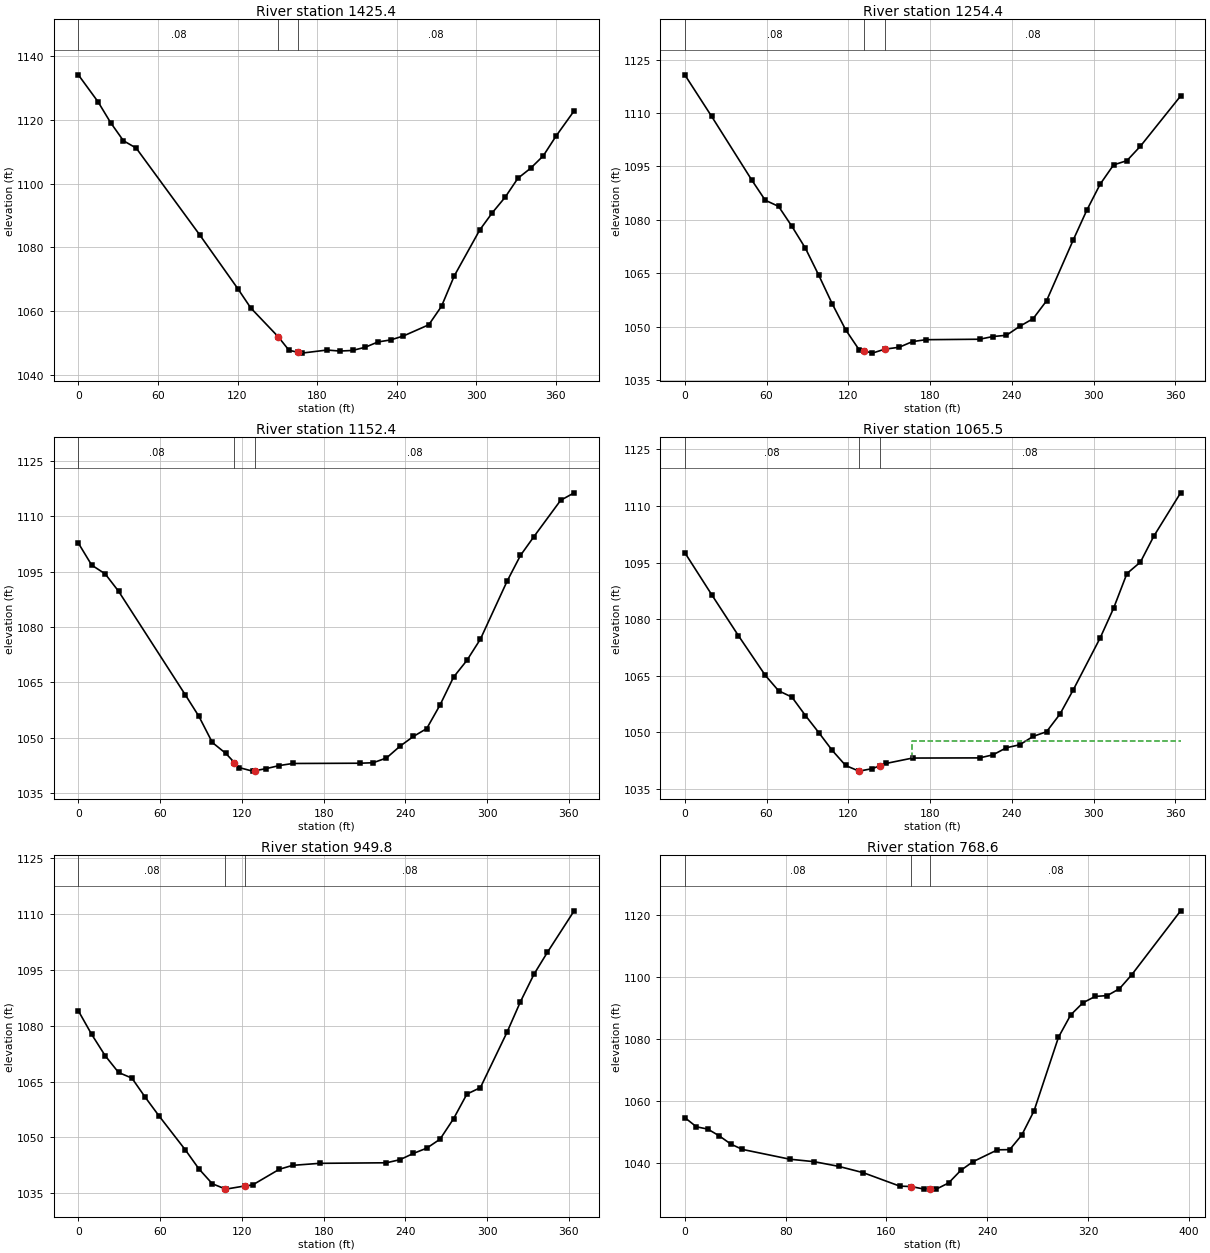
Type RM Length L Ch R = 1 ,1425.4  ,176.5,171,165.5
XS GIS Cut Line= 5
     1729310.992      314233.832     1729320.831      314222.835
     1729359.332      314179.805     1729557.502      313958.322
     1729560.253      313955.248
#Sta/Elev= 30
       0 1134.14    14.8  1125.7    24.4 1119.09      34 1113.44    43.6 1111.15
    91.7 1083.77   120.4 1066.89     130 1060.93   150.8 1051.84   158.8 1047.65
   165.8 1046.99   168.4 1046.75   187.5 1047.72   197.1  1047.4   206.7 1047.59
   216.3  1048.6   225.9 1050.26   235.5  1050.9   245.1 1052.14   264.2 1055.65
   273.8 1061.46   283.4 1070.99   302.6 1085.41   312.2 1090.89   321.8 1095.72
   331.4 1101.66   340.9 1104.78   350.5 1108.69   360.1 1114.88   373.8 1122.84
#Mann= 3 , 0 , 0
       0     .08       0   150.8    .045       0   165.8     .08       0
Bank Sta=150.8,165.8
XS Rating Curve= 0 ,0
Exp/Cntr=0.3,0.1

Type RM Length L Ch R = 1 ,1254.4  ,102,102,102.1
XS GIS Cut Line= 2
     1729479.397      314351.817     1729650.131      314030.604
#Sta/Elev= 30
       0 1120.71    19.7 1109.04    49.2 1091.14      59 1085.52    68.8 1083.79
    78.6 1078.18    88.5 1072.04    98.3 1064.46   108.2 1056.42     118 1049.17
   127.8  1043.6   131.6 1043.22   137.6  1042.6   146.6  1043.7   157.3 1044.25
   167.1 1045.84     177 1046.37   216.3  1046.5   226.1 1047.26     236 1047.61
   245.8 1050.14   255.6 1052.28   265.4 1057.27   285.1 1074.44     295 1082.74
   304.8 1090.04   314.6 1095.43   324.4 1096.62   334.3 1100.68   363.8 1114.77
#Mann= 3 , 0 , 0
       0     .08       0   131.6    .045       0   146.6     .08       0
Bank Sta=131.6,146.6
XS Rating Curve= 0 ,0
Exp/Cntr=0.3,0.1

Type RM Length L Ch R = 1 ,1152.4  ,86.9,86.9,87
XS GIS Cut Line= 2
     1729567.699      314398.752     1729738.432      314077.538
#Sta/Elev= 30
       0  1102.7     9.8 1096.73    19.7 1094.36    29.5 1089.67    78.6 1061.55
    88.5 1055.77    98.3 1048.72   108.2 1045.76   114.5 1043.28     118 1041.92
   127.8 1040.96   129.5 1041.07   137.6 1041.62   147.5 1042.47   157.3 1043.03
   206.5  1043.1   216.3 1043.23   226.1 1044.52     236  1047.7   245.8 1050.34
   255.6 1052.47   265.4 1058.87   275.3  1066.4   285.1 1070.94     295 1076.68
   314.6 1092.38   324.4 1099.35   334.3 1104.46   353.9 1114.28   363.8  1116.3
#Mann= 3 , 0 , 0
       0     .08       0   114.5    .045       0   129.5     .08       0
Bank Sta=114.5,129.5
XS Rating Curve= 0 ,0
Exp/Cntr=0.3,0.1

Type RM Length L Ch R = 1 ,1065.5  ,115.9,115.7,115.4
XS GIS Cut Line= 2
     1729639.852       314447.63     1729810.585      314126.416
#Sta/Elev= 30
       0 1097.63    19.7 1086.49    39.3 1075.62      59  1065.1    68.8 1060.98
    78.6 1059.29    88.5 1054.41    98.3 1049.88   108.2 1045.14     118 1041.15
   127.8 1039.65   128.1 1039.67   137.6 1040.31   143.1 1041.07   147.5 1041.68
   167.1 1043.12   216.3 1043.16   226.1 1043.97     236 1045.86   245.8 1046.65
   255.6 1048.87   265.4  1050.1   275.3  1054.8   285.1 1061.27   304.8 1075.02
   314.6 1082.86   324.4 1092.08   334.3 1095.12   344.1 1101.98   363.8  1113.5
#Mann= 3 , 0 , 0
       0     .08       0   128.1    .045       0   143.1     .08       0
#XS Ineff= 2 , 0
                          166.52          1047.7
Permanent Ineff=
       F       F
Bank Sta=128.1,143.1
XS Rating Curve= 0 ,0
Exp/Cntr=0.3,0.1

Type RM Length L Ch R = 1 ,949.8   ,186.2,181.1,172.9
XS GIS Cut Line= 2
     1729735.136      314501.547     1729905.869      314180.333
#Sta/Elev= 30
       0 1084.02     9.8 1077.67    19.7 1071.95    29.5 1067.45    39.3 1065.93
    49.2 1060.73      59 1055.87    78.6  1046.6    88.5 1041.53    98.3 1037.54
   107.3 1036.23   108.2  1036.1   122.3 1036.96   127.8 1037.21   147.5 1041.44
   157.3 1042.49     177 1043.03   226.1 1043.18     236 1044.01   245.8 1045.69
   255.6  1047.1   265.4 1049.52   275.3 1055.01   285.1 1061.64     295 1063.37
   314.6  1078.3   324.4 1086.47   334.3 1093.83   344.1 1099.69   363.8 1110.88
#Mann= 3 , 0 , 0
       0     .08       0   107.3    .045       0   122.3     .08       0
Bank Sta=107.3,122.3
XS Rating Curve= 0 ,0
Exp/Cntr=0.3,0.1

Type RM Length L Ch R = 1 ,768.6   ,182.7,189.7,199.9
XS GIS Cut Line= 3
     1729941.609       314577.14     1729946.096      314513.274
     1729969.176      314184.754
#Sta/Elev= 30
       0 1054.72     9.2 1051.75    18.3    1051    27.4 1048.81    36.6 1046.16
    45.7 1044.46    83.4  1041.3   102.8  1040.5   122.1    1039   141.5 1036.97
   170.6 1032.62   179.7  1032.5   189.9 1031.66   194.7 1031.67   199.6 1031.68
   209.3 1033.64     219 1037.72   228.7 1040.51   248.1 1044.33   257.8 1044.39
   267.4 1049.12   277.1 1056.89   296.5 1080.63   306.2 1087.82   315.9 1091.72
   325.6 1093.77   335.2 1094.04   344.9 1096.27   354.6 1100.75   393.4 1121.36
#Mann= 3 , 0 , 0
       0     .08       0   179.7    .045       0   194.7     .08       0
Bank Sta=179.7,194.7
XS Rating Curve= 0 ,0
Exp/Cntr=0.3,0.1

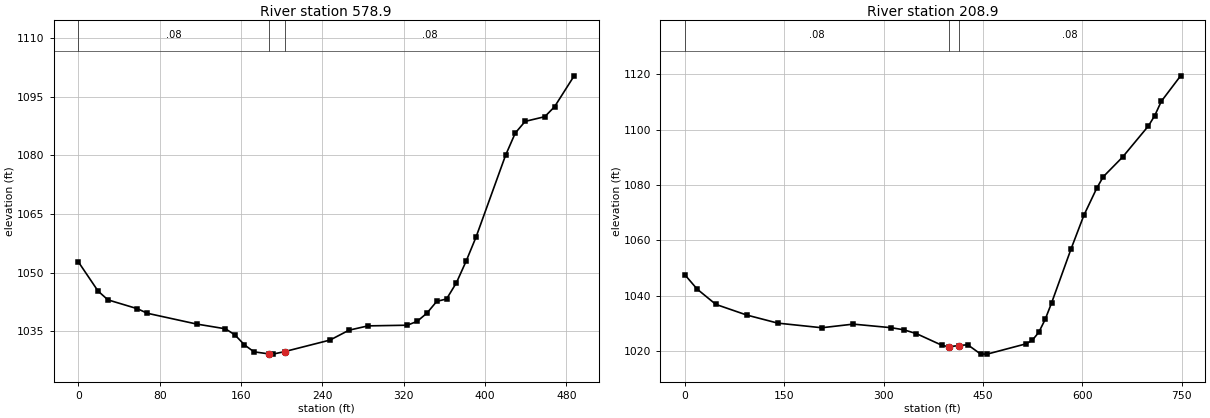
Type RM Length L Ch R = 1 ,578.9   ,347.8,370,392.3
XS GIS Cut Line= 4
     1729963.011      314596.225     1730074.732      314538.037
     1730158.917      314403.251     1730091.024      314212.185
#Sta/Elev= 30
       0 1052.77    19.4 1045.29    29.1 1043.04    58.1 1040.77    67.8 1039.61
   116.3 1036.85   144.7 1035.63     154 1034.07   163.4 1031.51   172.7 1029.74
   187.9 1029.19   191.4 1029.15   202.9  1029.8   247.5 1032.75   266.2 1035.28
   284.9 1036.38   323.5 1036.55   333.2 1037.54   342.8 1039.64   352.5 1042.66
   362.1 1043.26   371.8 1047.41   381.4 1052.97   391.1  1059.1   420.1 1080.01
   429.7 1085.74   439.4 1088.72   458.7 1089.92   468.3 1092.46   487.6 1100.38
#Mann= 3 , 0 , 0
       0     .08       0   187.9    .045       0   202.9     .08       0
Bank Sta=187.9,202.9
XS Rating Curve= 0 ,0
Exp/Cntr=0.3,0.1

Type RM Length L Ch R = 1 ,208.9   ,218.7,208.9,199.1
XS GIS Cut Line= 4
       1729989.8      314652.082     1730134.758      314614.959
     1730334.516      314676.831     1730723.427      314659.153
#Sta/Elev= 30
       0 1047.55    18.7 1042.33    46.8 1036.82    93.5 1032.96   140.3 1030.04
   206.7 1028.37   254.2 1029.68   311.2 1028.39   330.2 1027.64   349.2 1026.27
     388 1022.02   398.1 1021.48   413.1 1021.93   426.9 1022.22   446.4 1018.85
   456.1 1018.83   514.5 1022.53   524.2 1023.82     534 1026.69   543.7 1031.36
   553.4 1037.34   582.6 1056.76   602.1 1069.02   621.5 1078.81   631.3 1082.96
   660.5 1090.08   699.4 1101.31   709.1  1105.1   718.9 1110.23   748.1 1119.47
#Mann= 3 , 0 , 0
       0     .08       0   398.1    .045       0   413.1     .08       0
Bank Sta=398.1,413.1
XS Rating Curve= 0 ,0
Exp/Cntr=0.3,0.1

Chan Stop Cuts=-1
Use User Specified Reach Order=0
Composite Channel Slope=5